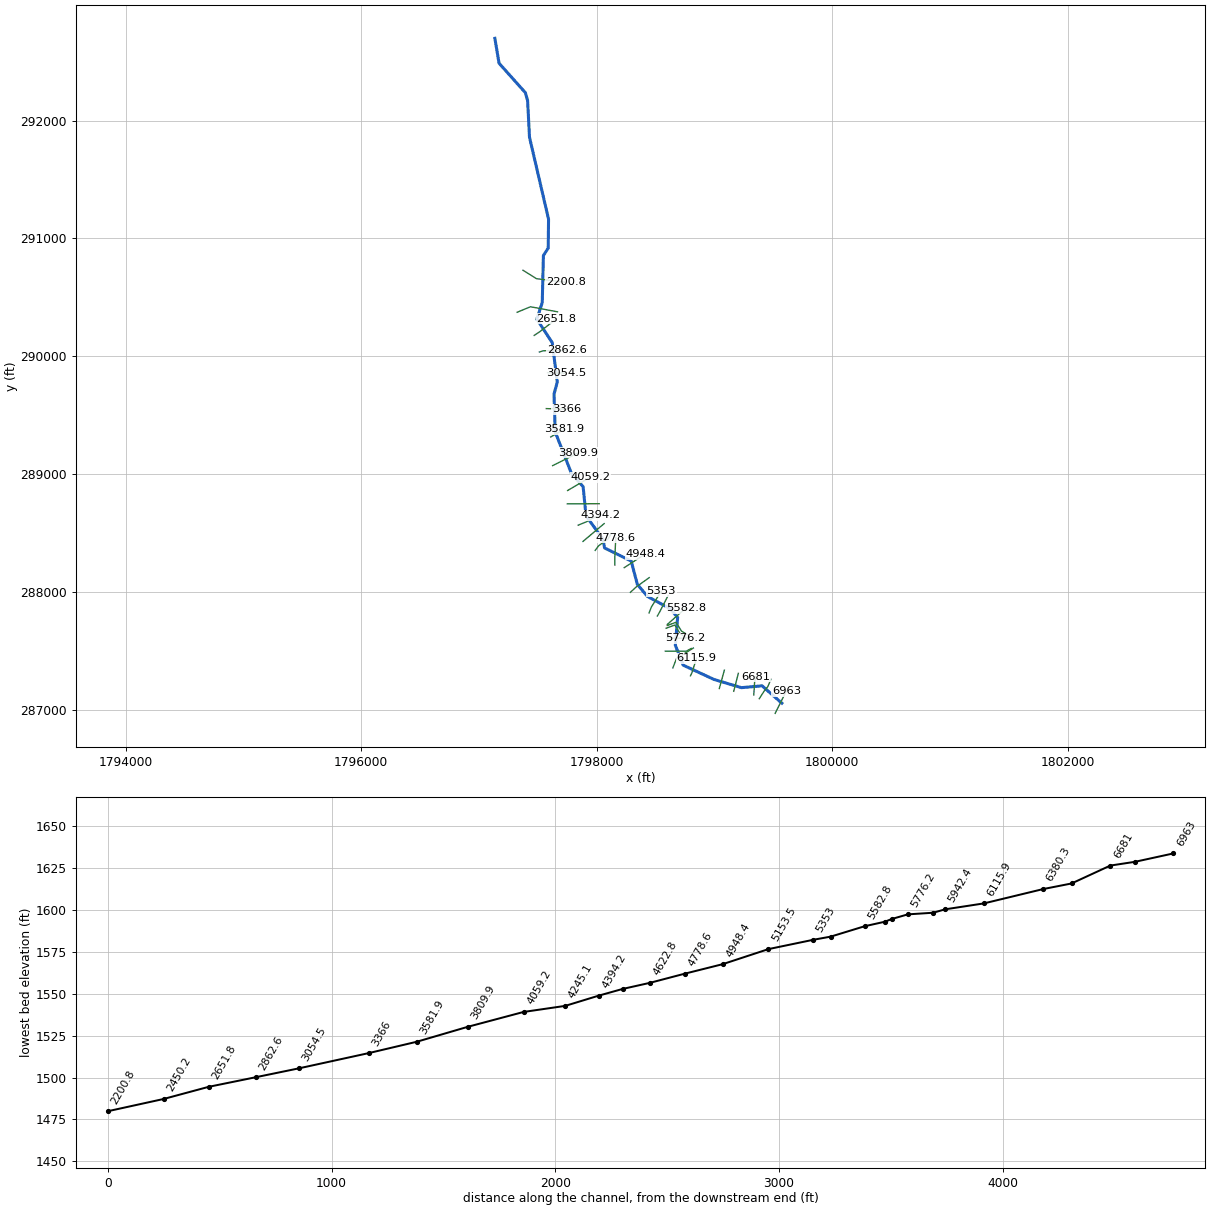
--- SKINFK.prj (project) ---

Proj Title=SKINFK
Current Plan=p01
Default Exp/Contr=0,0
English Units
Geom File=g01
Flow File=f01
Plan File=p01
BEGIN DESCRIPTION:
END DESCRIPTION:
DSS Export Rating Curves= 0
DSS Export Rating Curve Sorted= 0
DSS Export Volume Flow Curves= 0
DXF OffsetX= 0
DXF OffsetY= 0
DXF ScaleX= 0
DXF ScaleY= 0

--- SKINFK.p01 (plan) ---

Plan Title=Floodplain
Program Version=4.00
Geom File=g01
Flow File=f01
K Sum by GR=0
Std Step Tol=0.01
Critical Tol=0.01
Num of Std Step Trials=20
Max Error Tol=0.3
Flow Tol Ratio=0.001
Split Flow NTrial=30
Split Flow Tol=0.02
Split Flow Ratio=0.02
Log Output Level=0
Friction Slope Method=1
Unsteady Friction Slope Method=2
Unsteady Bridges Friction Slope Method=1
Global Log Level=0
CheckData=False
Run HTab=0
Run UNet=0
Run PostProcess=0
UNET Theta=0
UNET Theta Warmup=0
UNET ZTol=0
UNET ZSATol=0
UNET MxIter=0
UNET MaxInSteps=0
UNET DtIC=0
UNET DtMin=0
UNET MaxCRTS=0
UNET WFStab=0
UNET SFStab=0
UNET WFX=0
UNET SFX=0
UNET DSS MLevel=0
UNET DZMax Abort=0
UNET Convert EG Bridges=0
UNET Use Existing IB Tables=0
UNET Froude Limit=0
UNET Froude Power=0
Write IC File=0
Echo Input=False
Echo Output=False
Write Detailed=0

--- SKINFK.f01 (steady flow) ---

Flow Title=NFF Regression Equation
Program Version=4.00
Number of Profiles=1
Profile Names=P100yr
River Rch & RM=SKINFK,Main      ,6963
877.9485
River Rch & RM=SKINFK,Main      ,5889.5
946.5827
River Rch & RM=SKINFK,Main      ,3809.9
1019.734
River Rch & RM=SKINFK,Main      ,3054.5
1132.751
River Rch & RM=SKINFK,Main      ,492.2
1202.325
Boundary for River Rch & Prof#=SKINFK,Main      ,1
Up Type=0
Dn Type=3
Dn Slope=0.031733

--- SKINFK.g01 (geometry) ---

Geom Title=USGS 10m DEM
Program Version=4.10

River Reach=SKINFK          ,Main
Reach XY= 30
     1799571.667      287054.532     1799403.883      287201.675
     1799228.591      287186.285     1798995.052      287256.037
     1798734.248      287377.281     1798667.582      287546.031
     1798687.026      287782.768     1798622.443      287857.073
     1798430.776      287960.545     1798344.665      288063.323
     1798293.276      288260.198     1798066.193      288372.698
     1798054.387       288444.92     1797909.249      288644.643
     1797884.785      288892.213     1797786.044      289003.975
     1797648.137       289356.17      1797637.39      289677.803
     1797665.601      289780.885     1797622.443      290114.851
      1797491.99      290314.739      1797537.72      290455.545
     1797547.443      290854.156     1797588.415      290918.254
     1797591.193      291163.392     1797429.387      291859.087
     1797413.415      292169.642     1797394.781      292236.333
     1797171.054      292487.004     1797135.443      292698.289

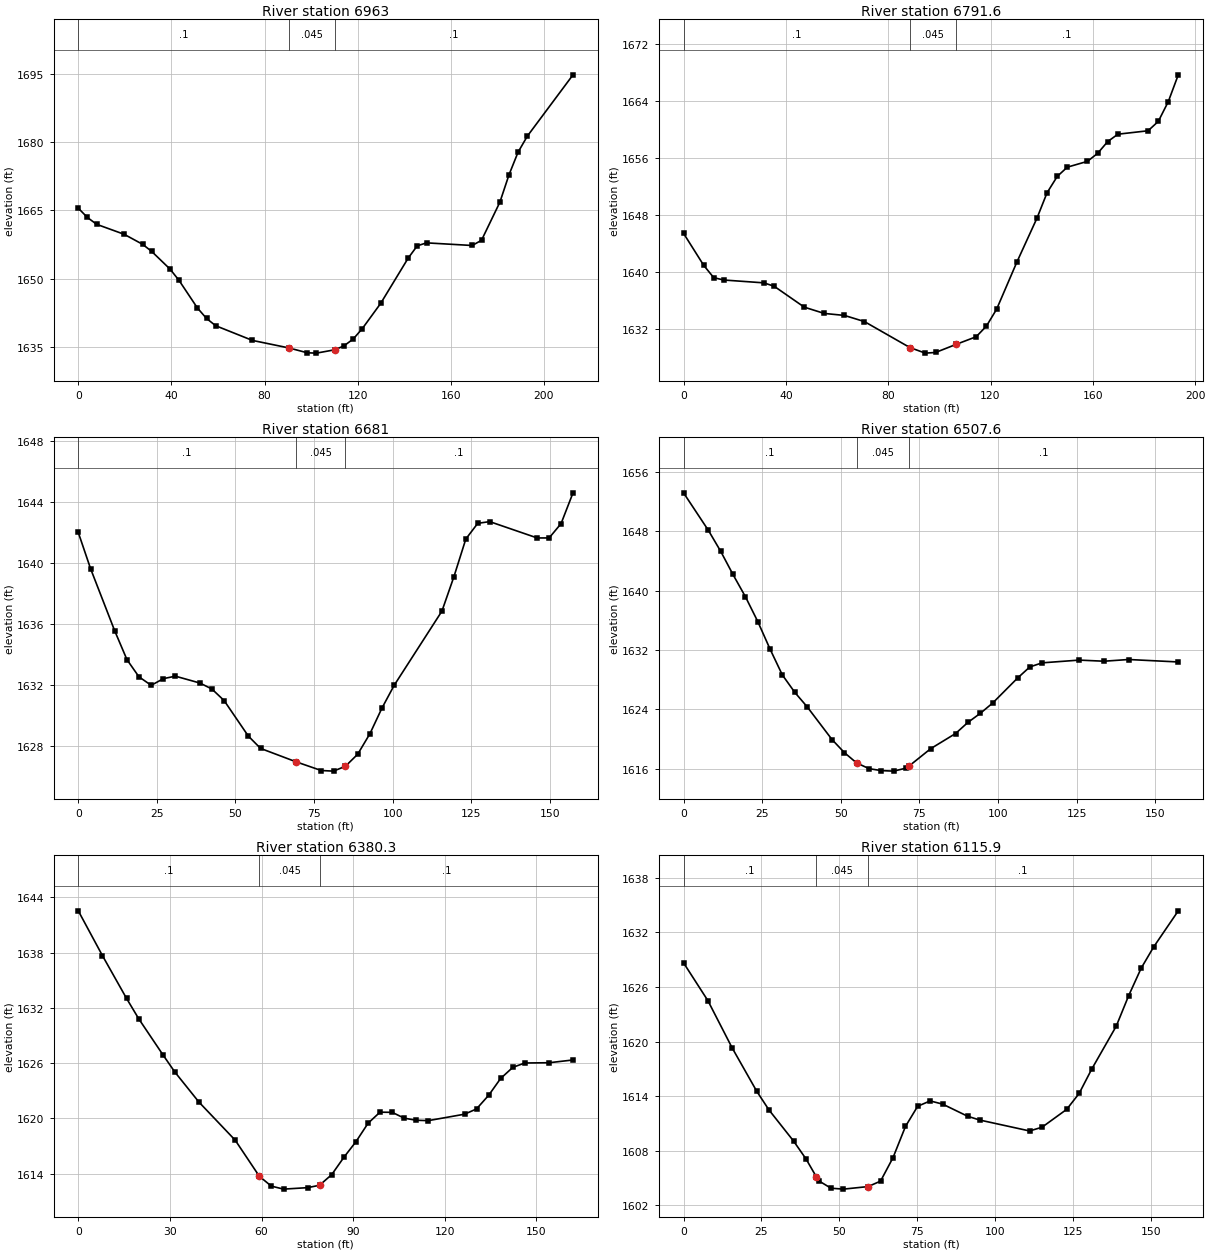
Type RM Length L Ch R = 1 ,6963    ,176,171.5,166.5
XS GIS Cut Line= 2
     1799514.755      286967.973     1799609.807      287158.077
#Sta/Elev= 30
       0 1665.51     3.9 1663.47     7.9 1661.95    19.7 1659.76    27.6 1657.56
    31.5    1656    39.4  1652.1    43.3 1649.59    51.2 1643.51    55.1 1641.22
      59 1639.63    74.8 1636.39    90.5 1634.73    98.4 1633.66   102.3 1633.59
   110.2 1634.33   114.1 1635.18   118.1  1636.7     122 1638.99   129.9 1644.55
   141.7 1654.51   145.6 1657.22   149.6 1657.87   169.2 1657.29   173.2 1658.44
   181.1 1666.84     185 1672.85   188.9 1677.84   192.9 1681.38   212.5 1694.87
#Mann= 3 , 0 , 0
       0      .1       0    90.5    .045       0   110.2      .1       0
Bank Sta=90.5,110.2
XS Rating Curve= 0 ,0
Exp/Cntr=0.3,0.1

Type RM Length L Ch R = 1 ,6791.6  ,96.5,110.6,124.8
XS GIS Cut Line= 4
     1799380.085      287092.568     1799420.232      287155.502
     1799452.784      287195.649     1799478.826      287257.498
#Sta/Elev= 30
       0  1645.4     7.9  1640.9    11.8 1639.18    15.7 1638.85    31.4 1638.45
    35.4 1637.98    47.2 1635.04      55 1634.16    62.9 1633.88    70.7 1633.02
    88.5 1629.37    94.5 1628.59    98.5 1628.68   106.5 1629.81   114.4 1630.89
   118.4 1632.38   122.4 1634.76   130.3 1641.36   138.2 1647.56   142.1 1651.09
   146.1 1653.39     150 1654.68   157.9  1655.5   161.9 1656.63   165.8 1658.27
   169.8 1659.31   181.6 1659.79   185.6 1661.11   189.5 1663.88   193.4 1667.64
#Mann= 3 , 0 , 0
       0      .1       0    88.5    .045       0   106.5      .1       0
Bank Sta=88.5,106.5
XS Rating Curve= 0 ,0
Exp/Cntr=0.3,0.1

Type RM Length L Ch R = 1 ,6681    ,176.1,173.3,168.3
XS GIS Cut Line= 3
     1799333.427      287124.035     1799339.937      287228.201
     1799349.703      287280.285
#Sta/Elev= 30
       0    1642     3.9 1639.63    11.6 1635.54    15.5 1633.65    19.3 1632.53
    23.2 1631.97    27.1 1632.41    30.9 1632.57    38.7 1632.12    42.5 1631.73
    46.4 1630.97    54.1 1628.64      58 1627.83    69.3 1626.95    77.3 1626.38
    81.2 1626.34      85 1626.66    88.9 1627.45    92.8  1628.8    96.6 1630.47
   100.5 1631.97   115.7 1636.84   119.5 1639.09   123.3 1641.57   127.1  1642.6
   130.9 1642.71     146 1641.64   149.8 1641.64   153.6 1642.58   157.4  1644.6
#Mann= 3 , 0 , 0
       0      .1       0    69.3    .045       0      85      .1       0
Bank Sta=69.3,85
XS Rating Curve= 0 ,0
Exp/Cntr=0.3,0.1

Type RM Length L Ch R = 1 ,6507.6  ,128.3,127.4,126.9
XS GIS Cut Line= 2
     1799163.192      287155.473     1799202.255      287307.817
#Sta/Elev= 30
       0 1653.17     7.9 1648.11    11.8  1645.3    15.7 1642.18    19.7 1639.15
    23.6 1635.83    27.5 1632.12    31.4 1628.64    35.4 1626.27    39.3 1624.34
    47.2 1619.93    51.1 1618.18      55 1616.78      59    1616    62.9 1615.74
    66.8 1615.67    70.8 1616.08    71.8 1616.39    78.6  1618.7    86.5 1620.74
    90.4 1622.23    94.4 1623.47    98.3 1624.85   106.2 1628.21   110.1 1629.71
     114 1630.26   125.8 1630.63   133.7 1630.48   141.5 1630.71   157.3 1630.38
#Mann= 3 , 0 , 0
       0      .1       0      55    .045       0    71.8      .1       0
Bank Sta=55,71.8
XS Rating Curve= 0 ,0
Exp/Cntr=0.3,0.1

Type RM Length L Ch R = 1 ,6380.3  ,265.1,264.3,263.4
XS GIS Cut Line= 2
     1799040.797       287178.91     1799083.765       287335.16
#Sta/Elev= 30
       0 1642.55     7.9 1637.69    15.8 1633.04    19.8 1630.82    27.7 1626.92
    31.6 1625.05    39.5 1621.78    51.4 1617.63    59.3 1613.71    63.2 1612.65
    67.2 1612.32    75.1 1612.48      79 1612.74      83  1613.9      87 1615.79
    90.9 1617.46    94.9 1619.48    98.8 1620.68   102.8 1620.66   106.7 1620.03
   110.7  1619.8   114.6 1619.76   126.5 1620.46   130.4 1621.03   134.4 1622.52
   138.3 1624.34   142.3 1625.55   146.2 1626.02   154.2 1626.05     162 1626.35
#Mann= 3 , 0 , 0
       0      .1       0    59.3    .045       0      79      .1       0
Bank Sta=59.3,79
XS Rating Curve= 0 ,0
Exp/Cntr=0.3,0.1

Type RM Length L Ch R = 1 ,6115.9  ,189.5,173.6,157.8
XS GIS Cut Line= 3
     1798796.005      287286.983     1798807.724      287311.723
     1798848.088      287436.723
#Sta/Elev= 30
       0 1628.65     7.8  1624.5    15.6  1619.3    23.5 1614.53    27.4 1612.49
    35.3 1609.07    39.3  1607.1    42.6 1605.14    43.3 1604.72    47.3 1603.89
    51.3 1603.79    59.2 1604.07    63.2 1604.67    67.2 1607.25    71.2 1610.68
    75.1 1612.89    79.1 1613.48    83.1 1613.13    91.1  1611.8      95 1611.38
     111 1610.18     115 1610.59   122.9 1612.55   126.9  1614.3   130.9 1616.95
   138.8 1621.69   142.8 1625.05   146.8 1628.06   150.8 1630.39   158.7 1634.36
#Mann= 3 , 0 , 0
       0      .1       0    42.6    .045       0    59.2      .1       0
Bank Sta=42.6,59.2
XS Rating Curve= 0 ,0
Exp/Cntr=0.3,0.1

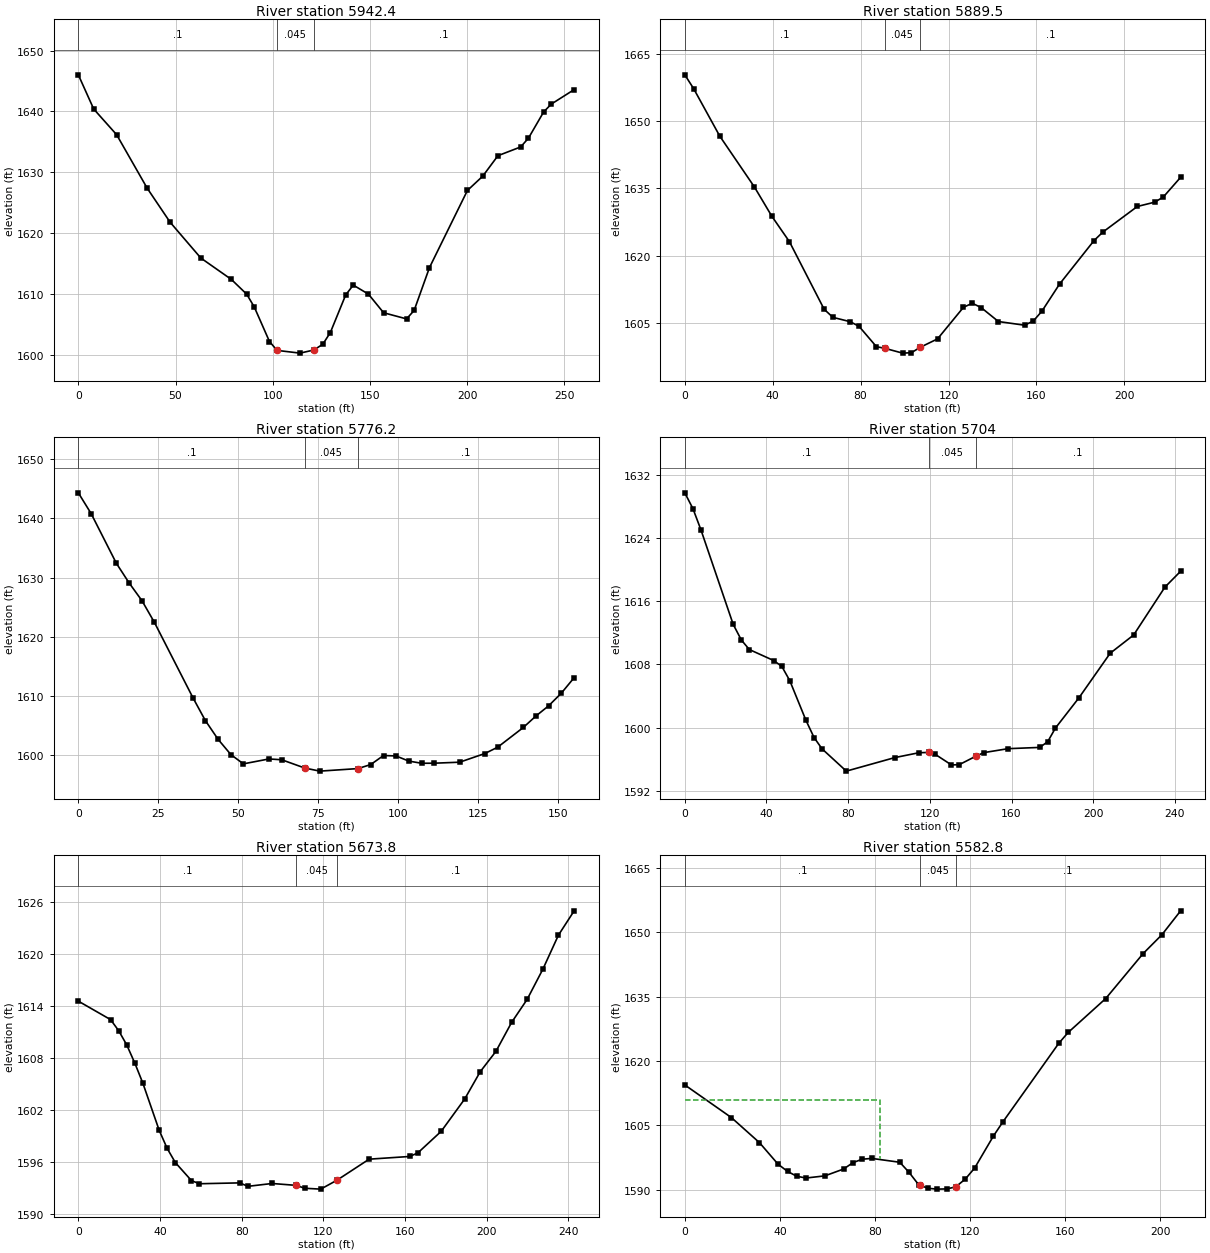
Type RM Length L Ch R = 1 ,5942.4  ,65.6,52.8,40.1
XS GIS Cut Line= 3
     1798646.265      287353.389     1798677.515      287434.119
     1798820.745       287522.66
#Sta/Elev= 30
       0 1646.02     7.9  1640.4    19.7 1636.17    35.4 1627.38    47.2 1621.78
      63 1615.89    78.7 1612.37    86.6 1609.94    90.5 1607.83    98.3 1602.16
   102.2  1600.7     114 1600.25   121.1 1600.76   125.7  1601.7   129.6 1603.63
   137.5 1609.82   141.4 1611.44   149.2 1609.95     157 1606.89   168.8 1605.88
   172.7 1607.27   180.6 1614.33   200.1    1627     208 1629.36   215.8 1632.72
   227.5 1634.16   231.5 1635.61   239.3 1639.91   243.2  1641.2     255 1643.59
#Mann= 3 , 0 , 0
       0      .1       0   102.2    .045       0   121.1      .1       0
Bank Sta=102.2,121.1
XS Rating Curve= 0 ,0
Exp/Cntr=0.3,0.1

Type RM Length L Ch R = 1 ,5889.5  ,113.3,113.3,112.9
XS GIS Cut Line= 3
     1798582.463      287496.619     1798760.849      287496.619
     1798802.515      287518.754
#Sta/Elev= 30
       0 1660.34       4 1657.28    15.9 1646.67    31.7 1635.29    39.6 1628.78
    47.6 1623.11    63.4 1608.02    67.4 1606.21    75.3 1605.24    79.3  1604.2
    87.2 1599.66    90.9 1599.32    99.1 1598.23   103.1 1598.32     107  1599.5
     115 1601.41   126.8 1608.46   130.8 1609.36   134.8 1608.41   142.7 1605.28
   154.6 1604.46   158.6 1605.41   162.5  1607.6   170.5 1613.63   186.2 1623.35
   190.2 1625.24   205.9 1630.96   213.8 1631.92   217.7 1633.06   225.6 1637.47
#Mann= 3 , 0 , 0
       0      .1       0    90.9    .045       0     107      .1       0
Bank Sta=90.9,107
XS Rating Curve= 0 ,0
Exp/Cntr=0.3,0.1

Type RM Length L Ch R = 1 ,5776.2  ,100,72.3,40.1
XS GIS Cut Line= 2
     1798598.088      287607.296     1798753.036      287605.994
#Sta/Elev= 30
       0 1644.33       4 1640.82    11.9  1632.4    15.9 1629.07    19.9 1626.08
    23.8  1622.4    35.8  1609.7    39.7 1605.82    43.7 1602.63    47.7 1600.05
    51.6 1598.49    59.6 1599.32    63.6 1599.18    70.8 1597.78    75.5 1597.26
    87.4 1597.69    91.4 1598.37    95.4  1599.9    99.3 1599.83   103.3 1598.96
   107.3 1598.59   111.2  1598.6   119.2 1598.77   127.1 1600.24   131.1 1601.31
   139.1 1604.64     143 1606.56     147  1608.3     151 1610.45     155 1613.07
#Mann= 3 , 0 , 0
       0      .1       0    70.8    .045       0    87.4      .1       0
Bank Sta=70.8,87.4
XS Rating Curve= 0 ,0
Exp/Cntr=0.3,0.1

Type RM Length L Ch R = 1 ,5704    ,36.5,30.2,34.5
XS GIS Cut Line= 4
     1798588.974      287690.629     1798663.192      287717.973
     1798708.765      287643.754      1798773.87      287603.389
#Sta/Elev= 30
       0 1629.69       4 1627.68     7.9 1625.01    23.7 1613.05    27.7 1611.07
    31.6 1609.87    43.5 1608.48    47.5 1607.74    51.4 1605.94    59.3 1600.93
    63.3 1598.74    67.2 1597.31    79.1 1594.49   102.8  1596.2   114.7 1596.82
   119.4 1596.85   122.6 1596.62   130.6 1595.27   134.4 1595.31   142.4 1596.36
   146.4 1596.83   158.3 1597.33   173.8 1597.49   177.7 1598.21   181.5 1599.94
     193 1603.76   208.3  1609.4   219.8 1611.71   235.1 1617.76   242.8 1619.77
#Mann= 3 , 0 , 0
       0      .1       0   119.4    .045       0   142.4      .1       0
Bank Sta=119.4,142.4
XS Rating Curve= 0 ,0
Exp/Cntr=0.3,0.1

Type RM Length L Ch R = 1 ,5673.8  ,40.2,91,135.3
XS GIS Cut Line= 4
      1798599.39      287714.067     1798673.609       287741.41
     1798719.182      287667.192     1798784.286      287626.827
#Sta/Elev= 30
       0 1614.53    15.8  1612.4    19.8 1611.11    23.7 1609.49    27.7 1607.37
    31.6 1605.08    39.6 1599.65    43.5 1597.57    47.5 1595.94    55.4 1593.86
    59.3  1593.5    79.1  1593.6      83  1593.2    94.9 1593.53   106.8 1593.31
   110.8 1592.98   118.7 1592.88   126.6  1593.9   142.4 1596.33   162.2 1596.64
   166.2 1597.04   177.7 1599.54   189.2 1603.26   196.8  1606.4   204.5 1608.75
   212.2 1612.09   219.8 1614.74   227.5 1618.22   235.1 1622.13   242.8 1624.93
#Mann= 3 , 0 , 0
       0      .1       0   106.8    .045       0   126.6      .1       0
Bank Sta=106.8,126.6
XS Rating Curve= 0 ,0
Exp/Cntr=0.3,0.1

Type RM Length L Ch R = 1 ,5582.8  ,143.3,151.6,160.2
XS GIS Cut Line= 3
      1798599.39      287723.181     1798622.828      287744.014
      1798755.64      287861.202
#Sta/Elev= 30
       0 1614.45    19.6 1606.84    31.4    1601    39.2 1595.99    43.2  1594.3
    47.1 1593.16      51 1592.76    58.9 1593.26    66.8 1594.86    70.7 1596.34
    74.6 1597.14    78.6 1597.33    90.4 1596.43    94.3 1594.08    98.3 1591.22
    98.9 1591.09   102.2 1590.37   106.1 1590.17   110.1 1590.22   113.9 1590.68
     118 1592.54   121.9  1595.1   129.8 1602.56   133.7 1605.79   157.3 1624.18
   161.2 1626.67     177 1634.58   192.7 1645.04   200.6 1649.43   208.5 1655.02
#Mann= 3 , 0 , 0
       0      .1       0    98.9    .045       0   113.9      .1       0
#XS Ineff= 2 , 0
           81.93 1610.89
Permanent Ineff=
       F       F
Bank Sta=98.9,113.9
XS Rating Curve= 0 ,0
Exp/Cntr=0.3,0.1

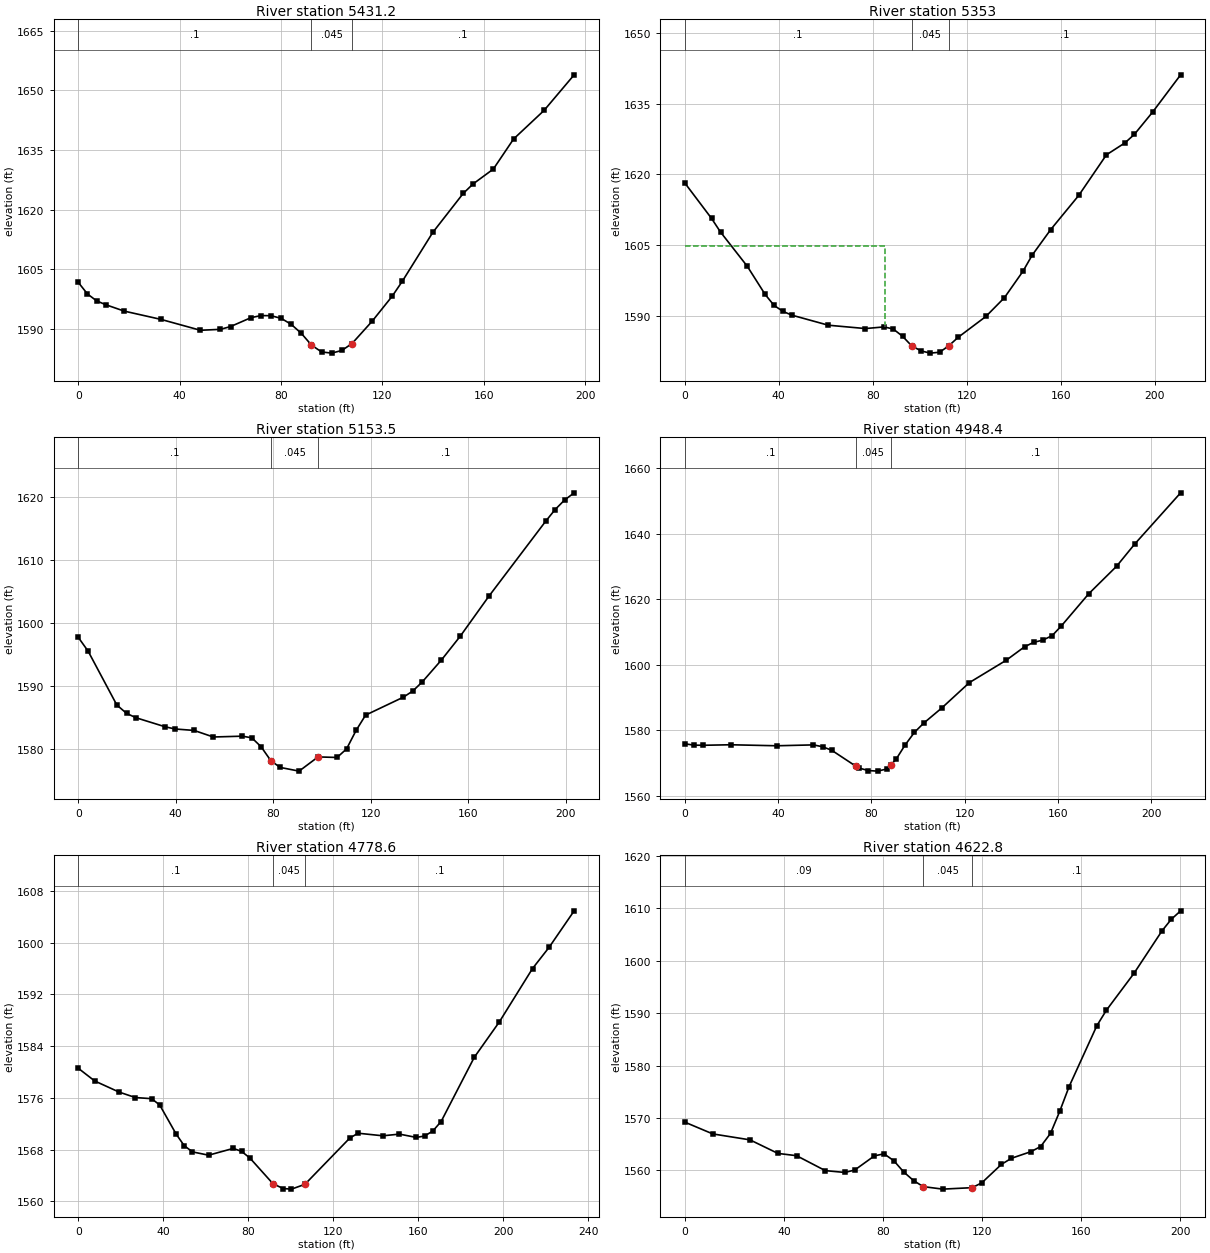
Type RM Length L Ch R = 1 ,5431.2  ,79.7,78.2,76
XS GIS Cut Line= 3
     1798514.755      287794.796     1798532.984      287826.046
     1798605.901      287967.973
#Sta/Elev= 30
       0 1601.74     3.6 1598.85     7.2 1597.12    10.8 1596.15    18.1 1594.54
    32.6 1592.46    48.2 1589.72    56.1 1589.96    60.1 1590.66    68.1 1592.88
    72.1 1593.42    76.1 1593.38    80.1 1592.71      84 1591.22      88 1588.96
      92 1586.01      96 1584.28     100 1583.98     104 1584.65     108 1586.37
     116 1592.02   123.9  1598.3   127.9 1602.06   139.9 1614.31   151.9  1624.1
   155.8 1626.49   163.8 1630.23   171.8 1637.79   183.8 1644.95   195.7 1653.91
#Mann= 3 , 0 , 0
       0      .1       0      92    .045       0     108      .1       0
Bank Sta=92,108
XS Rating Curve= 0 ,0
Exp/Cntr=0.3,0.1

Type RM Length L Ch R = 1 ,5353    ,208.1,199.5,190.6
XS GIS Cut Line= 3
     1798444.442      287820.837     1798463.974      287870.317
     1798547.307      288004.431
#Sta/Elev= 30
       0 1618.18    11.4 1610.65    15.2 1607.77    26.6 1600.51    34.2 1594.54
      38 1592.21    41.8 1590.94    45.6 1590.14    61.1 1588.01    76.9  1587.3
    84.8 1587.65    88.7 1587.22    92.7 1585.67    96.6 1583.63   100.6 1582.56
   104.5 1582.09   108.5 1582.28   112.4 1583.65   116.4 1585.45   128.2 1589.87
   136.1 1593.86     144 1599.47   147.9 1602.87   155.8  1608.3   167.7 1615.52
   179.5 1624.14   187.4 1626.68   191.4 1628.48   199.2 1633.22   211.1 1641.11
#Mann= 3 , 0 , 0
       0      .1       0    96.6    .045       0   112.4      .1       0
#XS Ineff= 2 , 0
           85.03 1604.91
Permanent Ineff=
       F       F
Bank Sta=96.6,112.4
XS Rating Curve= 0 ,0
Exp/Cntr=0.3,0.1

Type RM Length L Ch R = 1 ,5153.5  ,206.2,205.1,203.8
XS GIS Cut Line= 3
     1798285.588      287995.317     1798335.067      288040.889
     1798445.745      288120.317
#Sta/Elev= 30
       0 1597.71       4 1595.55    15.8 1587.02    19.8  1585.7    23.7    1585
    35.6 1583.58    39.6 1583.23    47.5    1583    55.4 1581.96    67.3 1582.09
    71.2 1581.83      75 1580.42      79 1578.22    82.8 1577.15    90.6 1576.56
    98.4 1578.81   106.2 1578.72   110.1 1580.08     114    1583   117.9 1585.42
   133.4 1588.26   137.3 1589.24   141.2 1590.69     149 1594.13   156.8 1597.93
   168.5 1604.23   191.8 1616.09   195.7 1617.95   199.6 1619.46   203.5 1620.59
#Mann= 3 , 0 , 0
       0      .1       0      79    .045       0    98.4      .1       0
Bank Sta=79,98.4
XS Rating Curve= 0 ,0
Exp/Cntr=0.3,0.1

Type RM Length L Ch R = 1 ,4948.4  ,148.4,169.8,191.2
XS GIS Cut Line= 2
     1798233.505      288204.952      1798411.89      288320.837
#Sta/Elev= 30
       0  1575.9     3.9 1575.48     7.9 1575.44    19.7  1575.6    39.4 1575.29
    55.2 1575.56    59.1 1574.99      63 1573.93    73.4 1569.05    74.8 1568.48
    78.8 1567.73    82.7 1567.56    86.7 1568.22    88.4 1569.49    90.6 1571.14
    94.5 1575.52    98.5 1579.37   102.4 1582.14   110.3 1586.85   122.1 1594.56
   137.9 1601.37   145.8  1605.5   149.7 1606.83   153.6  1607.5   157.6 1608.88
   161.5  1611.8   173.3 1621.65   185.2    1630     193 1636.79   212.7 1652.41
#Mann= 3 , 0 , 0
       0      .1       0    73.4    .045       0    88.4      .1       0
Bank Sta=73.4,88.4
XS Rating Curve= 0 ,0
Exp/Cntr=0.3,0.1

Type RM Length L Ch R = 1 ,4778.6  ,175.9,155.8,134.7
XS GIS Cut Line= 3
     1798154.078      288227.087     1798154.078      288296.098
      1798161.89       288460.16
#Sta/Elev= 30
       0 1580.57     7.7 1578.61    19.2 1576.89    26.8 1576.05    34.5 1575.87
    38.3 1574.89      46 1570.41    49.8 1568.61    53.7 1567.64    61.3 1567.13
    72.9 1568.18    76.8 1567.72    80.7  1566.7    91.6 1562.71    96.4 1561.97
   100.3 1561.88   106.6 1562.62   127.7 1569.77   131.6 1570.53   143.3 1570.13
   151.1 1570.39     159 1569.88   162.9 1570.09   166.8 1570.87   170.7 1572.34
   186.3 1582.27   198.1 1587.75   213.7    1596   221.5 1599.28   233.3 1604.93
#Mann= 3 , 0 , 0
       0      .1       0    91.6    .045       0   106.6      .1       0
Bank Sta=91.6,106.6
XS Rating Curve= 0 ,0
Exp/Cntr=0.3,0.1

Type RM Length L Ch R = 1 ,4622.8  ,119.4,121.1,122.5
XS GIS Cut Line= 4
     1797986.856      288351.248     1798016.153      288390.311
     1798096.448      288447.819     1798122.489      288493.392
#Sta/Elev= 30
       0  1569.2    11.3 1566.95    26.3 1565.82    37.6 1563.23    45.1  1562.8
    56.7 1559.95    64.6  1559.6    68.6 1560.07    76.5 1562.76    80.4 1563.16
    84.4 1561.82    88.3 1559.71    92.3 1558.06    96.2  1556.9   104.1 1556.42
     116  1556.7   119.9 1557.64   127.8 1561.15   131.8  1562.3   139.7 1563.57
   143.6 1564.54   147.6 1567.06   151.3 1571.25   155.1 1575.99   166.3  1587.6
   170.1 1590.52   181.3  1597.6   192.6  1605.7   196.3 1607.88   200.1 1609.51
#Mann= 3 , 0 , 0
       0     .09       0    96.2    .045       0     116      .1       0
Bank Sta=96.2,116
XS Rating Curve= 0 ,0
Exp/Cntr=0.3,0.1

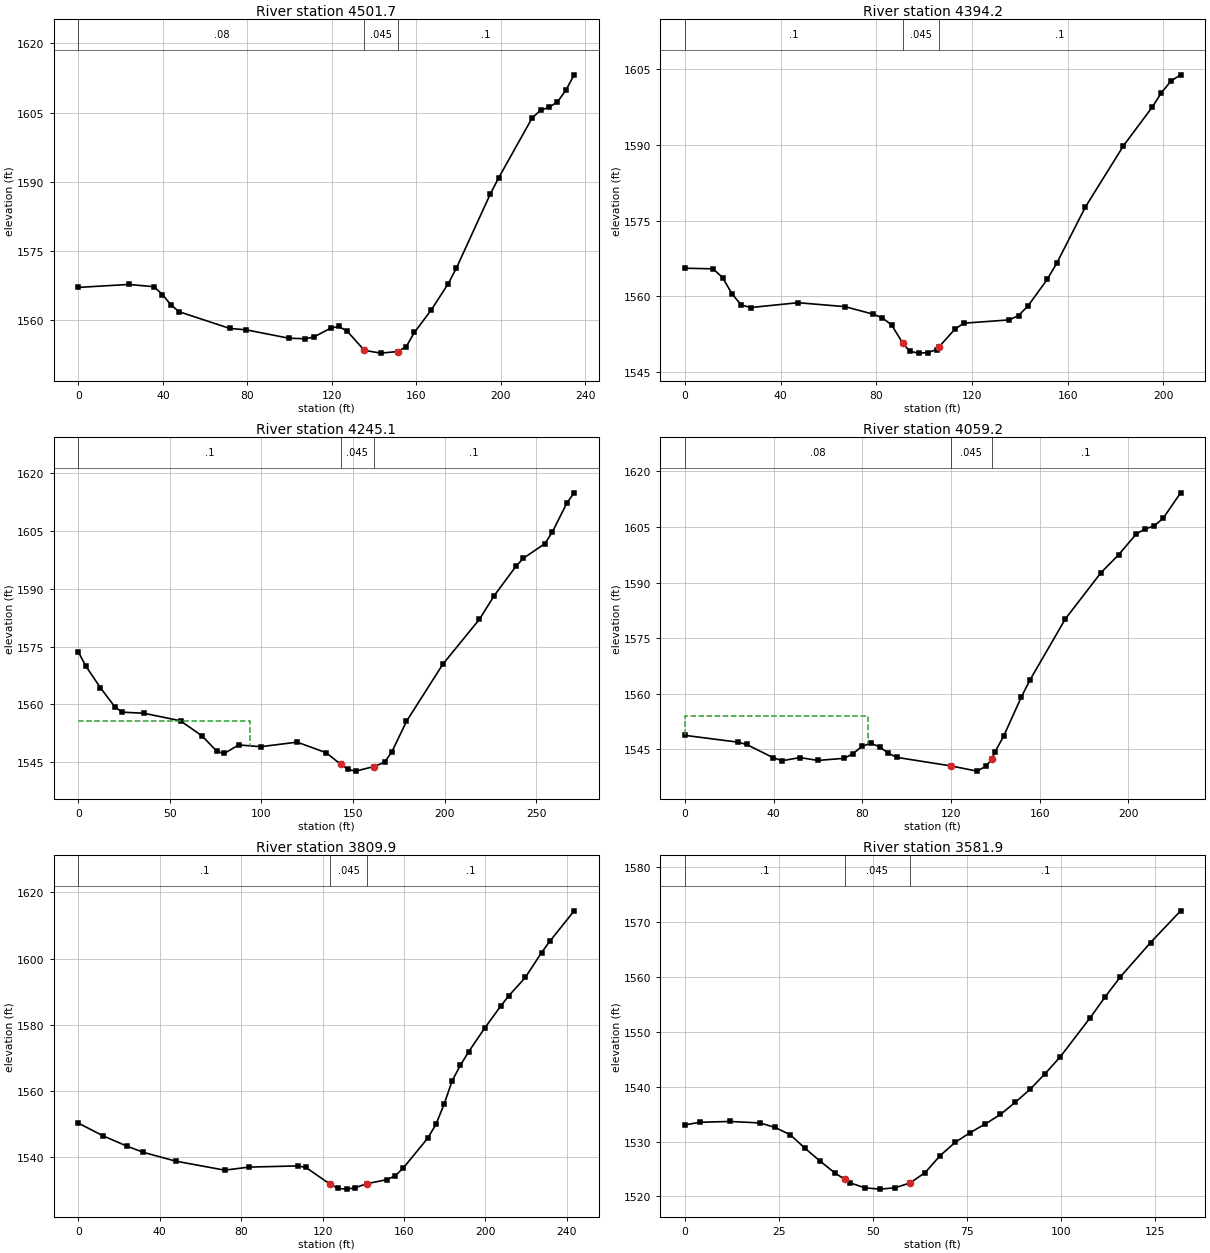
Type RM Length L Ch R = 1 ,4501.7  ,111.5,107.5,104.2
XS GIS Cut Line= 2
     1797883.245      288427.608     1798062.932       288578.65
#Sta/Elev= 30
       0 1567.07    23.9 1567.71    35.8 1567.22    39.8 1565.52    43.8  1563.3
    47.7 1561.79    71.6 1558.18    79.6 1557.85    99.5 1556.06   107.4 1555.92
   111.4 1556.29   119.4 1558.22   123.3  1558.6   127.3 1557.55   135.4 1553.41
   143.2 1552.81   151.2 1553.16   155.2  1554.2   159.1 1557.32   167.1  1562.2
   175.1 1567.89     179  1571.3     195 1587.32   198.9 1590.79   214.8 1603.82
   218.8 1605.52   222.8 1606.15   226.8 1607.31   230.8 1609.87   234.7 1613.19
#Mann= 3 , 0 , 0
       0     .08       0   135.4    .045       0   151.2      .1       0
Bank Sta=135.4,151.2
XS Rating Curve= 0 ,0
Exp/Cntr=0.3,0.1

Type RM Length L Ch R = 1 ,4394.2  ,161,149.1,136.5
XS GIS Cut Line= 4
      1797842.88      288565.629     1797915.797      288595.577
     1797963.974      288625.525     1798031.682      288648.962
#Sta/Elev= 30
       0 1565.58    11.8 1565.46    15.8 1563.74    19.7 1560.51    23.6  1558.3
    27.6 1557.81    47.3 1558.76      67 1557.98    78.8 1556.48    82.6 1555.74
    86.4 1554.38    91.1 1550.73      94 1549.16    97.7 1548.79   101.5 1548.89
   105.3  1549.5   106.1 1549.95   112.9 1553.54   116.6 1554.71   135.6 1555.36
   139.5 1556.23   143.5 1558.17   151.5  1563.4   155.5 1566.63   167.4 1577.68
   183.3 1589.78   195.3 1597.41   199.2  1600.3   203.2 1602.61   207.2 1603.82
#Mann= 3 , 0 , 0
       0      .1       0    91.1    .045       0   106.1      .1       0
Bank Sta=91.1,106.1
XS Rating Curve= 0 ,0
Exp/Cntr=0.3,0.1

Type RM Length L Ch R = 1 ,4245.1  ,173.7,185.9,197.5
XS GIS Cut Line= 2
     1797750.432      288746.619     1798021.265      288747.921
#Sta/Elev= 30
       0 1573.61       4 1569.98      12 1564.36    19.9 1559.39    23.9 1557.99
    35.8 1557.71    55.8 1555.75    67.7 1551.79    75.7 1547.81    79.7 1547.29
    87.6  1549.5    99.6 1549.04   119.5 1550.22   135.4 1547.47   143.4 1544.44
   147.4 1543.14   151.4 1542.71   161.3 1543.88   167.3 1545.02   171.3 1547.77
   179.2  1555.6   199.1 1570.43   219.1 1582.08     227 1588.09     239 1595.79
     243 1597.85   254.9 1601.68   258.9  1604.7   266.8 1612.17   270.8 1614.83
#Mann= 3 , 0 , 0
       0      .1       0   143.4    .045       0   161.3      .1       0
#XS Ineff= 2 , 0
           93.61 1555.81
Permanent Ineff=
       F       F
Bank Sta=143.4,161.3
XS Rating Curve= 0 ,0
Exp/Cntr=0.3,0.1

Type RM Length L Ch R = 1 ,4059.2  ,250.5,249.2,246.6
XS GIS Cut Line= 2
     1797753.036        288859.9     1797945.745      288973.181
#Sta/Elev= 30
       0 1548.76      24 1546.92    27.9 1546.29    39.9 1542.71    43.9 1541.91
    51.9 1542.76    59.9 1541.99    71.8 1542.55    75.8  1543.8    79.8 1545.75
    83.8 1546.63    87.8 1545.67    91.8 1543.89    95.8 1542.79   119.8 1540.52
   131.7  1539.1   135.7 1540.41   138.4 1542.32   139.7 1544.16   143.7 1548.51
   151.7 1559.12   155.7 1563.82   171.6 1580.25   187.6 1592.69   195.6 1597.54
   203.6  1603.2   207.6  1604.5   211.6 1605.31   215.6 1607.35   223.5 1614.24
#Mann= 3 , 0 , 0
       0     .08       0   119.8    .045       0   138.4      .1       0
#XS Ineff= 2 , 0
           82.74 1554.01
Permanent Ineff=
       F       F
Bank Sta=119.8,138.4
XS Rating Curve= 0 ,0
Exp/Cntr=0.3,0.1

Type RM Length L Ch R = 1 ,3809.9  ,226.7,228,229.2
XS GIS Cut Line= 2
     1797625.866      289071.054     1797843.626      289180.241
#Sta/Elev= 30
       0 1550.23      12 1546.42      24 1543.22      32 1541.37    47.9 1538.71
    71.9 1535.99    83.9 1536.92   107.8 1537.27   111.8 1536.81   123.8  1531.7
   127.8 1530.44   131.8 1530.25   135.8 1530.63   141.7 1531.89   151.8 1533.14
   155.7 1534.31   159.7 1536.67   171.7  1545.7   175.7 1549.85   179.7 1555.93
   183.7  1563.1   187.7  1567.7   191.7 1571.76   199.7 1579.02   207.7 1585.78
   211.6 1588.82   219.6 1594.28   227.6 1601.82   231.6  1605.2   243.6 1614.45
#Mann= 3 , 0 , 0
       0      .1       0   123.8    .045       0   141.7      .1       0
Bank Sta=123.8,141.7
XS Rating Curve= 0 ,0
Exp/Cntr=0.3,0.1

Type RM Length L Ch R = 1 ,3581.9  ,228.3,215.9,203.4
XS GIS Cut Line= 2
     1797609.807      289314.327      1797724.39      289379.431
#Sta/Elev= 30
       0 1533.03       4 1533.51      12 1533.66      20 1533.39      24 1532.57
      28 1531.25      32 1528.76    35.9 1526.47    39.9 1524.29    42.5 1523.12
    43.9 1522.49    47.9 1521.57    51.9 1521.34    55.9 1521.59    59.9 1522.47
    63.9 1524.36    67.9 1527.46    71.9 1529.87    75.9 1531.65    79.9 1533.21
    83.9 1534.93    87.9 1537.18    91.8 1539.52    95.8 1542.38    99.8 1545.42
   107.8 1552.58   111.8  1556.4   115.8    1560   123.8 1566.23   131.8 1572.01
#Mann= 3 , 0 , 0
       0      .1       0    42.5    .045       0    59.9      .1       0
Bank Sta=42.5,59.9
XS Rating Curve= 0 ,0
Exp/Cntr=0.3,0.1

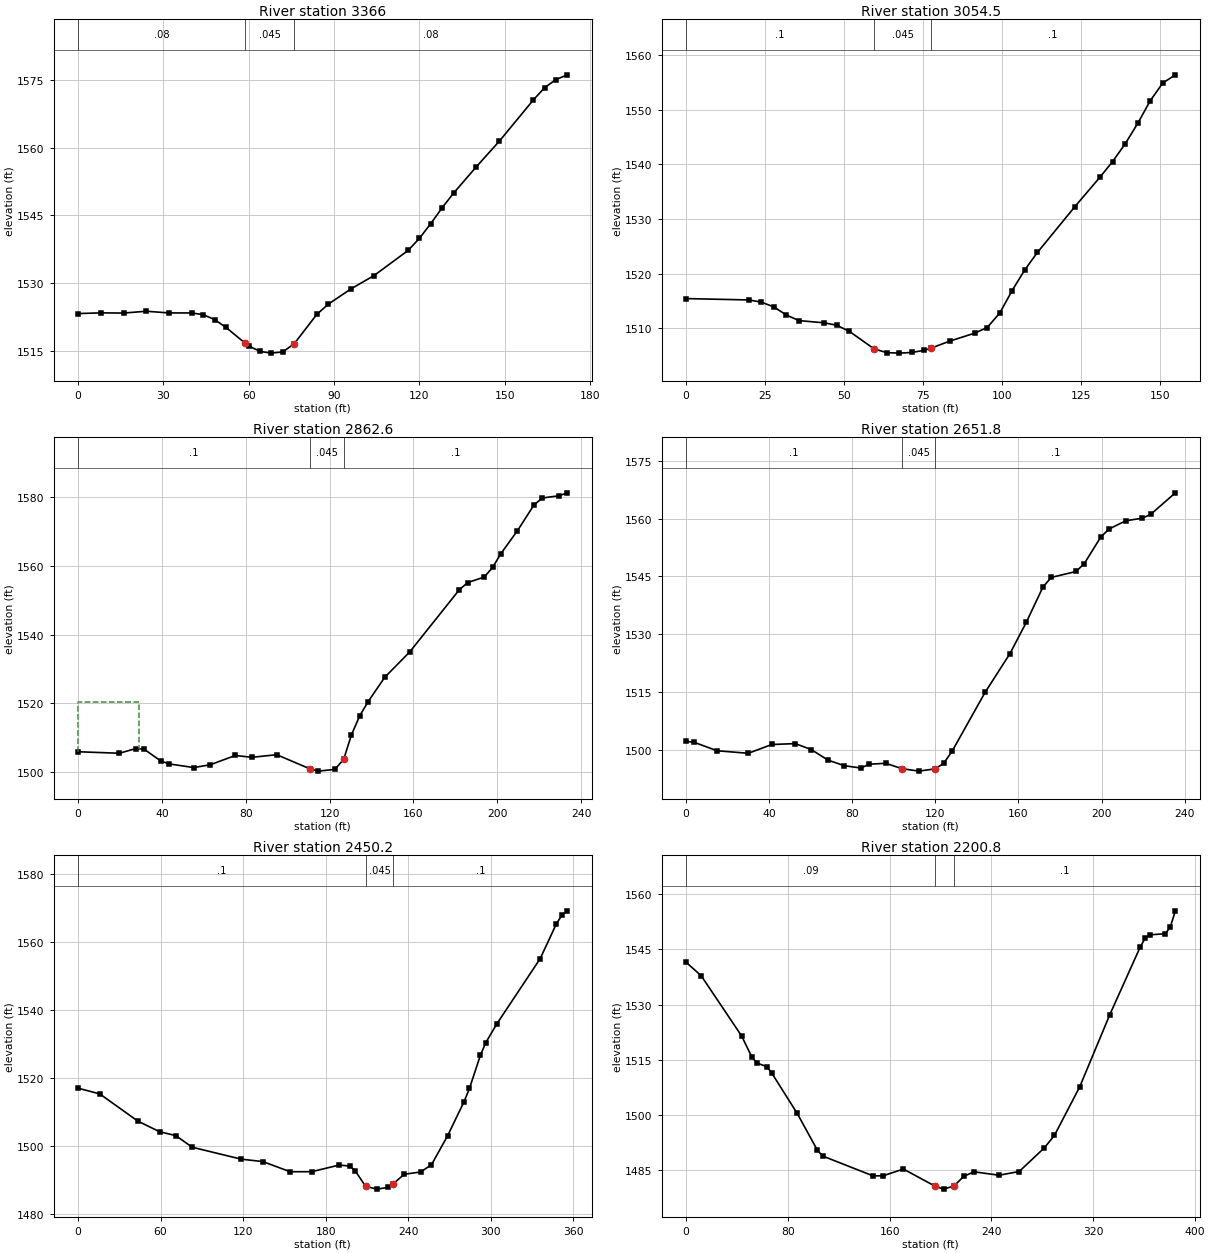
Type RM Length L Ch R = 1 ,3366    ,310.7,311.5,310.7
XS GIS Cut Line= 2
     1797572.047      289555.212     1797743.922      289550.004
#Sta/Elev= 30
       0 1523.29       8 1523.44      16  1523.4      24  1523.8      32 1523.43
      40 1523.42      44 1523.04      48 1521.97      52 1520.23    58.7 1516.76
      60 1516.11      64 1514.92      68 1514.54      72 1514.82      76 1516.62
      84 1523.16      88 1525.38      96 1528.77     104 1531.67     116 1537.24
     120 1539.92     124  1543.2     128  1546.7     132 1549.92     140 1555.75
     148 1561.35     160  1570.5     164 1573.25     168 1575.04     172 1576.08
#Mann= 3 , 0 , 0
       0     .08       0    58.7    .045       0      76     .08       0
Bank Sta=58.7,76
XS Rating Curve= 0 ,0
Exp/Cntr=0.3,0.1

Type RM Length L Ch R = 1 ,3054.5  ,190.8,191.9,193.1
XS GIS Cut Line= 2
     1797582.463        289859.9     1797737.411      289855.994
#Sta/Elev= 30
       0 1515.45    19.9  1515.2    23.8 1514.81    27.8 1513.93    31.8 1512.44
    35.8 1511.42    43.7 1511.02    47.7 1510.58    51.7 1509.47    59.6 1506.24
    63.6 1505.56    67.6 1505.47    71.5 1505.59    75.5 1505.99    77.6 1506.38
    83.5 1507.66    91.4 1509.12    95.4 1510.15    99.4 1512.82   103.3 1516.92
   107.3  1520.7   111.3 1523.89   123.2 1532.29   131.2 1537.72   135.1 1540.51
   139.1 1543.76   143.1 1547.52     147 1551.61     151 1554.89     155 1556.39
#Mann= 3 , 0 , 0
       0      .1       0    59.6    .045       0    77.6      .1       0
Bank Sta=59.6,77.6
XS Rating Curve= 0 ,0
Exp/Cntr=0.3,0.1

Type RM Length L Ch R = 1 ,2862.6  ,196,210.8,225.1
XS GIS Cut Line= 3
     1797513.453      290035.681     1797547.307      290046.098
     1797745.224      290050.004
#Sta/Elev= 30
       0 1505.85    19.7 1505.41    27.6 1506.78    31.5  1506.6    39.4 1503.19
    43.3 1502.32    55.2 1501.24    63.1 1502.06      75 1504.76    82.9 1504.23
    94.8 1504.98   110.6 1500.87   114.6  1500.2   122.5 1500.71   126.7 1503.63
   130.4 1510.76   134.4 1516.39   138.4 1520.48   146.3 1527.56   158.2 1534.94
   181.9  1553.1   185.9 1555.17   193.8 1556.79   197.7 1559.57   201.7 1563.61
   209.6 1570.29   217.5 1577.82   221.5 1579.82   229.4 1580.47   233.4 1581.32
#Mann= 3 , 0 , 0
       0      .1       0   110.6    .045       0   126.7      .1       0
#XS Ineff= 2 , 0
           29.25 1520.25
Permanent Ineff=
       F       F
Bank Sta=110.6,126.7
XS Rating Curve= 0 ,0
Exp/Cntr=0.3,0.1

Type RM Length L Ch R = 1 ,2651.8  ,220.1,201.6,180.1
XS GIS Cut Line= 3
     1797469.182      290176.306     1797516.057      290207.556
     1797657.984      290316.931
#Sta/Elev= 30
       0 1502.18     3.8 1501.97      15 1499.75      30  1499.1    41.3 1501.38
    52.6 1501.61    60.3 1500.06    68.3 1497.33    76.2 1495.88    84.2 1495.27
    88.2 1496.27    96.2  1496.5   103.8 1495.12   112.1 1494.47     120 1495.07
     124  1496.5     128 1499.58   143.9 1514.87   155.9 1524.96   163.8 1533.12
   171.8 1542.26   175.8 1544.73   187.7 1546.26   191.7 1548.33   199.7 1555.29
   203.7  1557.3   211.6 1559.42   219.6 1560.09   223.6 1561.07   235.5 1566.67
#Mann= 3 , 0 , 0
       0      .1       0   103.8    .045       0     120      .1       0
Bank Sta=103.8,120
XS Rating Curve= 0 ,0
Exp/Cntr=0.3,0.1

Type RM Length L Ch R = 1 ,2450.2  ,248,249.4,250.7
XS GIS Cut Line= 3
     1797324.651      290372.921     1797437.932      290419.796
     1797667.099      290376.827
#Sta/Elev= 30
       0 1516.92    15.8 1515.24    43.5 1507.23    59.3 1504.11    71.2 1502.95
      83 1499.55   118.6 1496.04   134.4 1495.32   154.2 1492.34     170 1492.35
   189.8  1494.3   197.7 1494.01   201.6 1492.58   209.1 1488.03   217.4 1487.22
   225.4 1487.72   229.3 1488.84   237.2  1491.6   249.1 1492.26     257  1494.4
   268.8 1502.98   280.7 1512.97   284.6 1516.85   292.5 1526.54   296.5 1530.35
   304.4 1535.78     336 1555.02   347.8 1565.27   351.8 1567.81   355.8  1569.1
#Mann= 3 , 0 , 0
       0      .1       0   209.1    .045       0   229.3      .1       0
Bank Sta=209.1,229.3
XS Rating Curve= 0 ,0
Exp/Cntr=0.3,0.1

Type RM Length L Ch R = 1 ,2200.8  ,155.1,158,160.5
XS GIS Cut Line= 3
      1797374.13      290729.692     1797488.713      290658.077
     1797736.109      290626.827
#Sta/Elev= 30
       0 1541.49    11.9 1537.83    43.7 1521.48    51.7 1515.78    55.6 1514.15
    63.6 1513.13    67.6 1511.29    87.4 1500.45   103.3 1490.45   107.3 1488.91
     147 1483.51   154.9 1483.54   170.8 1485.37   195.6 1480.74   202.4 1479.92
   210.6 1480.79   218.2 1483.36   226.2 1484.62     246 1483.69   261.8  1484.7
   281.6 1491.13   289.5 1494.51   309.3 1507.64     333 1527.26   356.8 1545.54
   360.7 1547.96   364.7 1548.91   376.6 1549.21   380.5 1551.02   384.5 1555.42
#Mann= 3 , 0 , 0
       0     .09       0   195.6    .045       0   210.6      .1       0
Bank Sta=195.6,210.6
XS Rating Curve= 0 ,0
Exp/Cntr=0.3,0.1