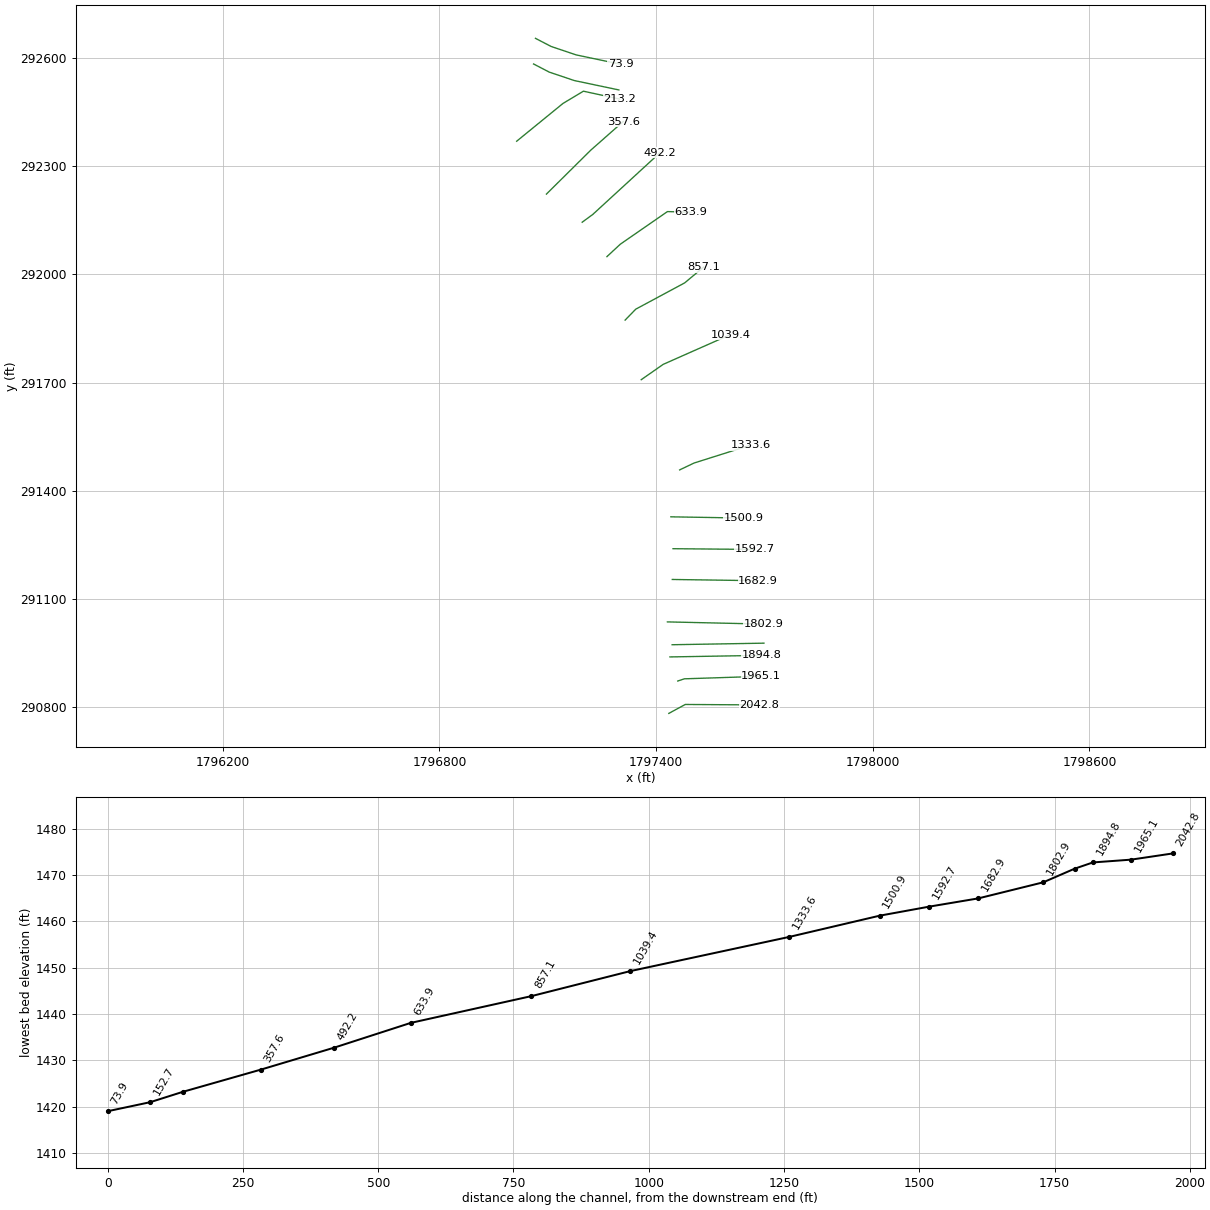
HEC-RAS study SKINFK.prj: SKINFK

--- SKINFK.g01 (geometry) --- (continued)

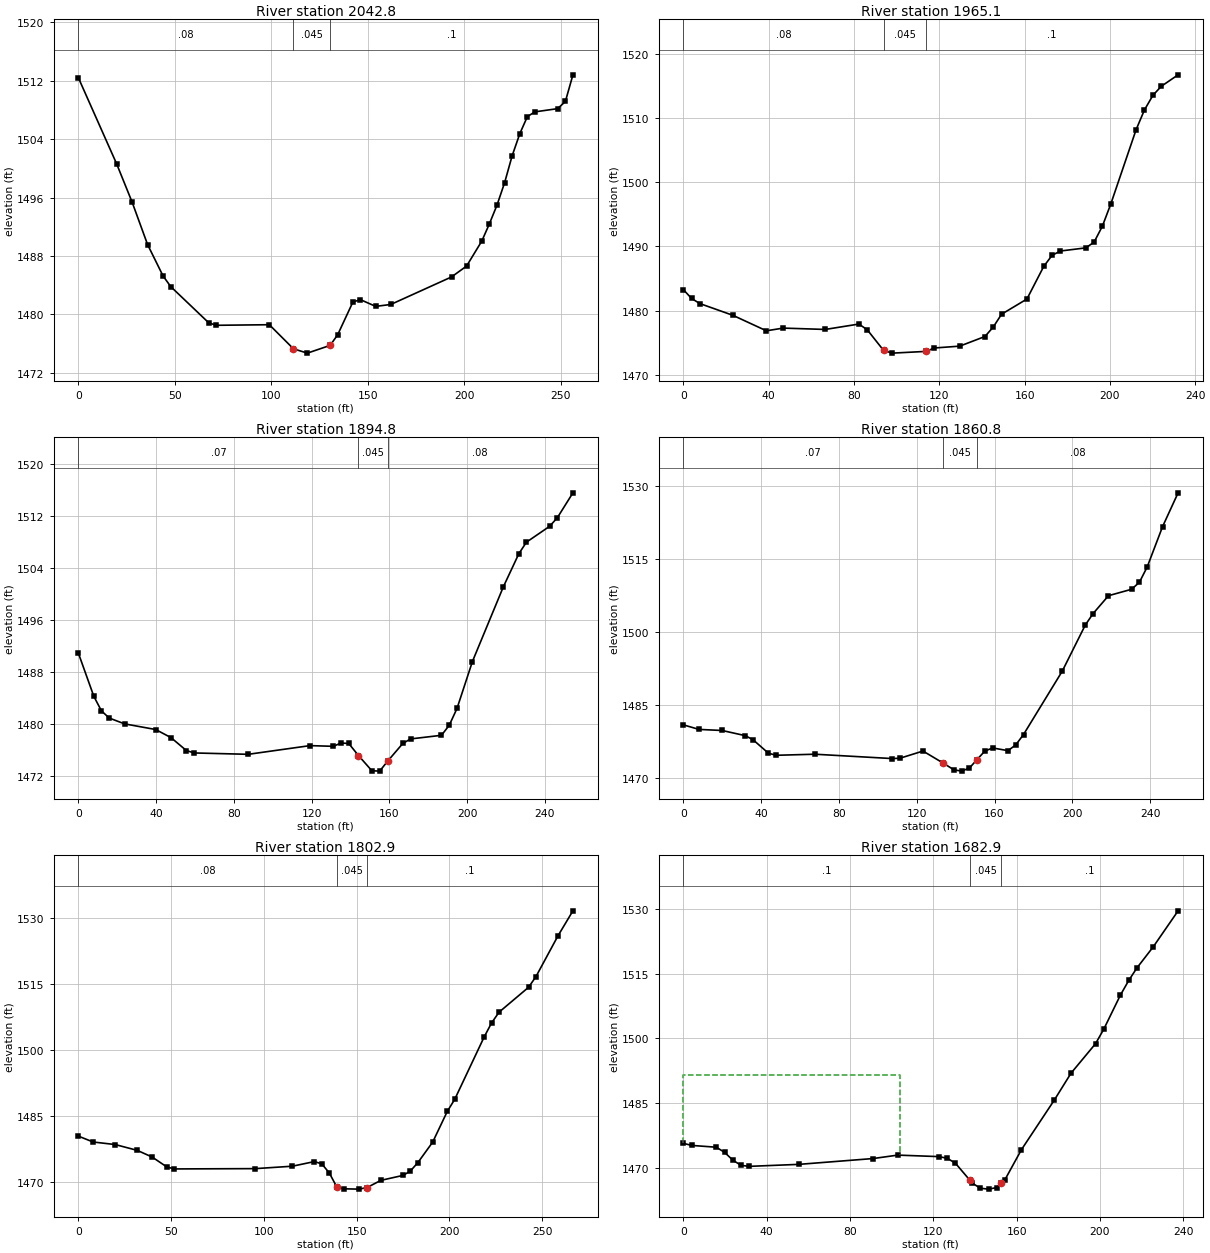
Type RM Length L Ch R = 1 ,2042.8  ,74.8,77.7,82.6
XS GIS Cut Line= 3
     1797435.328      290781.775     1797480.901      290806.514
     1797685.328      290805.212
#Sta/Elev= 30
       0 1512.44    19.9 1500.61    27.9 1495.38    35.9 1489.58    43.9 1485.29
    47.9 1483.82    67.6 1478.86    71.5 1478.52      99  1478.6   111.5  1475.3
   118.7 1474.71   130.5 1475.77   134.4 1477.22   142.3 1481.71   146.2 1482.03
   154.1 1481.11   161.9 1481.37   193.4 1485.14   201.2 1486.63   209.1 1490.06
     213  1492.4     217    1495   220.9 1498.04   224.8 1501.72   228.8 1504.77
   232.7 1507.09   236.6 1507.74   248.4 1508.18   252.4 1509.17   256.3 1512.81
#Mann= 3 , 0 , 0
       0     .08       0   111.5    .045       0   130.5      .1       0
Bank Sta=111.5,130.5
XS Rating Curve= 0 ,0
Exp/Cntr=0.3,0.1

Type RM Length L Ch R = 1 ,1965.1  ,72.8,70.3,66
XS GIS Cut Line= 3
     1797460.067      290871.619     1797478.297      290877.695
      1797690.97      290884.639
#Sta/Elev= 30
       0 1483.24     3.8 1481.88     7.7 1481.08    23.2 1479.25    38.9 1476.84
    46.8 1477.26    66.5 1477.05    82.3 1477.89    86.2    1477    93.9 1473.77
      98 1473.36   113.8 1473.63   117.7 1474.16   129.6 1474.45   141.4 1475.95
   145.3 1477.42   149.2 1479.42   161.1 1481.79     169 1486.88   172.9  1488.6
   176.8 1489.27   188.7 1489.76   192.6 1490.65   196.5 1493.15   200.5 1496.66
   212.3 1508.17   216.2 1511.24   220.2 1513.53   224.1 1514.93     232 1516.72
#Mann= 3 , 0 , 0
       0     .08       0    93.9    .045       0   113.8      .1       0
Bank Sta=93.9,113.8
XS Rating Curve= 0 ,0
Exp/Cntr=0.3,0.1

Type RM Length L Ch R = 1 ,1894.8  ,33.9,34,33.9
XS GIS Cut Line= 2
     1797438.366      290938.459     1797692.706      290942.799
#Sta/Elev= 30
       0 1490.98       8 1484.28    11.9 1482.05    15.9 1480.94    23.8 1480.04
    39.8 1479.17    47.7 1477.92    55.6 1475.93    59.6 1475.56    87.4 1475.35
   119.2 1476.69   131.2 1476.58   135.1 1477.09   139.1 1477.02   144.1 1475.16
     151 1472.82     155 1472.76   159.1 1474.29   166.9 1477.02   170.9 1477.72
   186.8 1478.28   190.8 1479.83   194.8 1482.43   202.7 1489.64   218.6 1501.14
   226.6 1506.26   230.5 1508.03   242.4 1510.47   246.4  1511.8   254.4 1515.63
#Mann= 3 , 0 , 0
       0     .07       0   144.1    .045       0   159.1     .08       0
Bank Sta=144.1,159.1
XS Rating Curve= 0 ,0
Exp/Cntr=0.3,0.1

Type RM Length L Ch R = 1 ,1860.8  ,58.8,57.9,57
XS GIS Cut Line= 2
     1797444.442      290972.313     1797698.783      290976.653
#Sta/Elev= 30
       0 1480.89       8 1479.96    19.9 1479.74    31.8 1478.68    35.8 1477.84
    43.7 1475.08    47.7 1474.65    67.6 1474.87   107.3 1473.98   111.3 1474.04
   123.2 1475.52   133.5 1473.07   139.1 1471.67   143.1  1471.4   147.1 1472.04
     151 1473.78     155 1475.51     159 1476.16   166.9  1475.6   170.9 1476.78
   174.9 1478.91   194.8  1491.9   206.7  1501.4   210.7 1503.74   218.6  1507.4
   230.5 1508.72   234.5 1510.16   238.5 1513.29   246.4 1521.56   254.4 1528.51
#Mann= 3 , 0 , 0
       0     .07       0   133.5    .045       0     151     .08       0
Bank Sta=133.5,151
XS Rating Curve= 0 ,0
Exp/Cntr=0.3,0.1

Type RM Length L Ch R = 1 ,1802.9  ,119.6,120,120
XS GIS Cut Line= 2
     1797431.422      291035.681     1797697.915      291029.605
#Sta/Elev= 30
       0 1480.49       8 1479.15    19.9 1478.57    31.8 1477.25    39.8 1475.74
    47.7  1473.5    51.7 1473.04    95.5 1473.11   115.4 1473.66   127.3 1474.71
   131.3 1474.17   135.3 1472.12   139.2 1469.05   143.2 1468.53   151.2 1468.46
   155.6 1468.81   163.1 1470.45   175.1 1471.58     179 1472.57     183 1474.46
     191 1479.11   198.9  1486.1   202.9 1488.83   218.8 1503.01   222.8 1506.18
   226.8  1508.6   242.7 1514.24   246.7 1516.68   258.6 1525.95   266.6 1531.58
#Mann= 3 , 0 , 0
       0     .08       0   139.2    .045       0   155.6      .1       0
Bank Sta=139.2,155.6
XS Rating Curve= 0 ,0
Exp/Cntr=0.3,0.1

Type RM Length L Ch R = 1 ,1682.9  ,90.3,90.2,89.9
XS GIS Cut Line= 2
     1797444.842      291153.462     1797682.342       291149.99
#Sta/Elev= 30
       0 1475.62       4 1475.14    15.8 1474.72    19.8 1473.51    23.8 1471.68
    27.7 1470.51    31.7 1470.28    55.4 1470.74      91 1472.09   102.9 1472.89
   122.7 1472.54   126.7 1472.15   130.6    1471   137.5 1467.07   138.6 1466.42
   142.5  1465.2   146.5 1464.99   150.4 1465.35   152.5 1466.33   154.4 1467.21
   162.3 1474.17   178.1  1485.7   186.1 1491.92   197.9 1498.79   201.9 1502.22
   209.8 1510.05   213.8 1513.45   217.7 1516.34   225.6 1521.28   237.5 1529.62
#Mann= 3 , 0 , 0
       0      .1       0   137.5    .045       0   152.5      .1       0
#XS Ineff= 2 , 0
          104.07 1491.43
Permanent Ineff=
       F       F
Bank Sta=137.5,152.5
XS Rating Curve= 0 ,0
Exp/Cntr=0.3,0.1

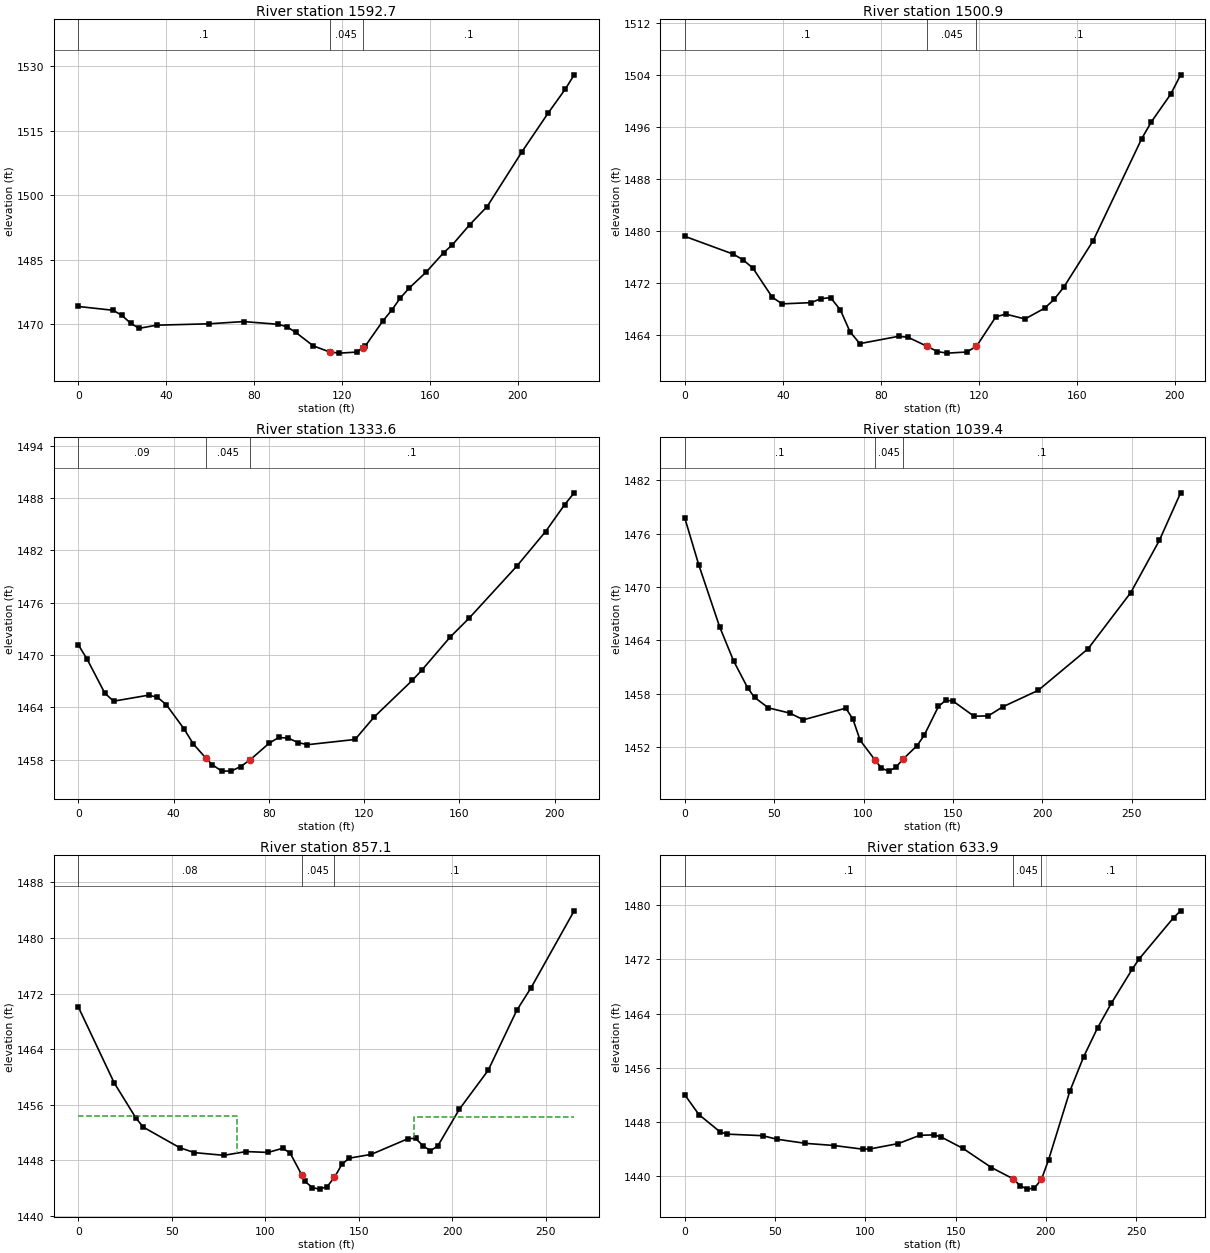
Type RM Length L Ch R = 1 ,1592.7  ,91.8,91.8,92.1
XS GIS Cut Line= 2
     1797446.925      291238.878      1797672.62      291236.795
#Sta/Elev= 30
       0 1474.07    15.8 1473.19    19.8 1472.02    23.8 1470.17    27.7 1468.99
    35.6 1469.72    59.4 1470.04    75.2 1470.56    91.1 1469.92      95 1469.34
      99 1468.04   106.9 1464.92   114.5 1463.47   118.8 1463.22   126.7 1463.46
   129.5 1464.48   130.7 1464.92   138.6 1470.69   142.6 1473.18   146.5    1476
   150.5  1478.3   158.4  1482.1   166.3 1486.59   170.3 1488.44   178.2 1493.12
   186.1 1497.32     202 1510.11   213.8 1519.02   221.7 1524.66   225.7 1527.96
#Mann= 3 , 0 , 0
       0      .1       0   114.5    .045       0   129.5      .1       0
Bank Sta=114.5,129.5
XS Rating Curve= 0 ,0
Exp/Cntr=0.3,0.1

Type RM Length L Ch R = 1 ,1500.9  ,157.7,167.3,174.1
XS GIS Cut Line= 2
      1797440.97      291327.348     1797643.227      291323.876
#Sta/Elev= 30
       0 1479.21    19.8 1476.47    23.8 1475.59    27.8 1474.32    35.7 1469.84
    39.7 1468.83    51.6 1469.02    55.5 1469.63    59.5 1469.78    63.5 1467.88
    67.4 1464.55    71.4 1462.72    87.3 1463.85    91.2 1463.68    98.9  1462.3
   103.1 1461.49   107.1 1461.26     115 1461.43     119 1462.31   126.9 1466.83
   130.9 1467.26   138.8 1466.51   146.8 1468.16   150.7 1469.52   154.7 1471.44
   166.6 1478.53   186.4  1494.2   190.4 1496.83   198.3 1501.08   202.3 1504.03
#Mann= 3 , 0 , 0
       0      .1       0    98.9    .045       0     119      .1       0
Bank Sta=98.9,119
XS Rating Curve= 0 ,0
Exp/Cntr=0.3,0.1

Type RM Length L Ch R = 1 ,1333.6  ,293.8,294.2,296.3
XS GIS Cut Line= 3
     1797465.276      291457.556     1797505.206      291476.653
     1797661.456      291526.132
#Sta/Elev= 30
       0 1471.15     3.7  1469.5    11.1 1465.62    14.8 1464.69    29.5 1465.38
    33.2 1465.14    36.9  1464.3    44.3 1461.55    48.3 1459.78    53.6 1458.15
    56.2 1457.42    60.2 1456.67    64.2 1456.68    68.2  1457.2    72.2 1457.98
    80.2 1459.89    84.2 1460.53    88.2 1460.45    92.2 1459.95    96.2  1459.7
   116.2  1460.3   124.2 1462.87   140.2 1467.07   144.2 1468.24   156.2 1472.06
   164.2 1474.24   184.2  1480.2   196.2 1484.14   204.2 1487.22   208.2 1488.58
#Mann= 3 , 0 , 0
       0     .09       0    53.6    .045       0    72.2      .1       0
Bank Sta=53.6,72.2
XS Rating Curve= 0 ,0
Exp/Cntr=0.3,0.1

Type RM Length L Ch R = 1 ,1039.4  ,179.7,182.2,183.8
XS GIS Cut Line= 3
     1797358.939       291707.99     1797419.703      291750.525
     1797605.467       291832.99
#Sta/Elev= 30
       0 1477.76     7.8  1472.5    19.5 1465.51    27.3 1461.68    35.1 1458.67
      39 1457.57    46.8 1456.39    58.6 1455.81    66.4 1455.05    90.1 1456.36
    94.1  1455.1    98.1 1452.74   106.5  1450.5     110 1449.61     114 1449.27
     118 1449.68     122  1450.6     130 1452.15     134 1453.33   141.9 1456.55
   145.9 1457.23   149.9 1457.18   161.8 1455.45   169.8 1455.49   177.8  1456.5
   197.7 1458.36   225.6 1463.04   249.5 1469.37   265.5 1475.24   277.4  1480.6
#Mann= 3 , 0 , 0
       0      .1       0   106.5    .045       0     122      .1       0
Bank Sta=106.5,122
XS Rating Curve= 0 ,0
Exp/Cntr=0.3,0.1

Type RM Length L Ch R = 1 ,857.1   ,220.1,223.2,224
XS GIS Cut Line= 4
     1797314.234      291873.355     1797343.748      291903.737
     1797479.165      291976.653     1797532.116      292020.924
#Sta/Elev= 30
       0 1470.07    19.2 1459.15    30.8  1454.1    34.7  1452.8    54.2 1449.84
    62.1 1449.13    77.8 1448.74    89.7 1449.28   101.5 1449.16   109.4 1449.76
   113.3 1449.05   119.5 1445.93   121.2    1445   125.2 1444.09   129.1 1443.88
   133.1 1444.25     137 1445.57     141 1447.46   144.9 1448.33   156.7 1448.88
   176.4 1451.14   180.4 1451.18   184.3 1450.12   188.3 1449.41   192.2 1450.06
   203.8 1455.37   219.2 1460.96   234.5 1469.59   242.2 1472.86   265.2  1483.9
#Mann= 3 , 0 , 0
       0     .08       0   119.5    .045       0     137      .1       0
#XS Ineff= 2 , 0
           84.79 1454.46  179.59         1454.23
Permanent Ineff=
       F       F
Bank Sta=119.5,137
XS Rating Curve= 0 ,0
Exp/Cntr=0.3,0.1

Type RM Length L Ch R = 1 ,633.9   ,139.4,141.8,146.9
XS GIS Cut Line= 4
     1797263.887       292049.57     1797301.213      292084.292
     1797431.422       292174.57     1797496.526      292172.834
#Sta/Elev= 30
       0 1452.01     7.8  1449.1    19.6 1446.53    23.5 1446.21    43.1 1445.98
      51 1445.46    66.8 1444.85    82.7 1444.53    98.5 1443.99   102.5 1444.02
   118.3 1444.82   130.2 1446.04   138.1  1446.1   142.1 1445.77     154 1444.11
   169.8 1441.28   181.7 1439.63   185.7 1438.61   189.6 1438.09   193.6 1438.24
   197.5 1439.52   201.5 1442.44   213.2 1452.52   220.9 1457.64   228.6  1461.9
   236.2 1465.52   247.7 1470.52   251.6 1472.07   270.7 1478.17   274.6 1479.18
#Mann= 3 , 0 , 0
       0      .1       0   181.7    .045       0   197.5      .1       0
Bank Sta=181.7,197.5
XS Rating Curve= 0 ,0
Exp/Cntr=0.3,0.1

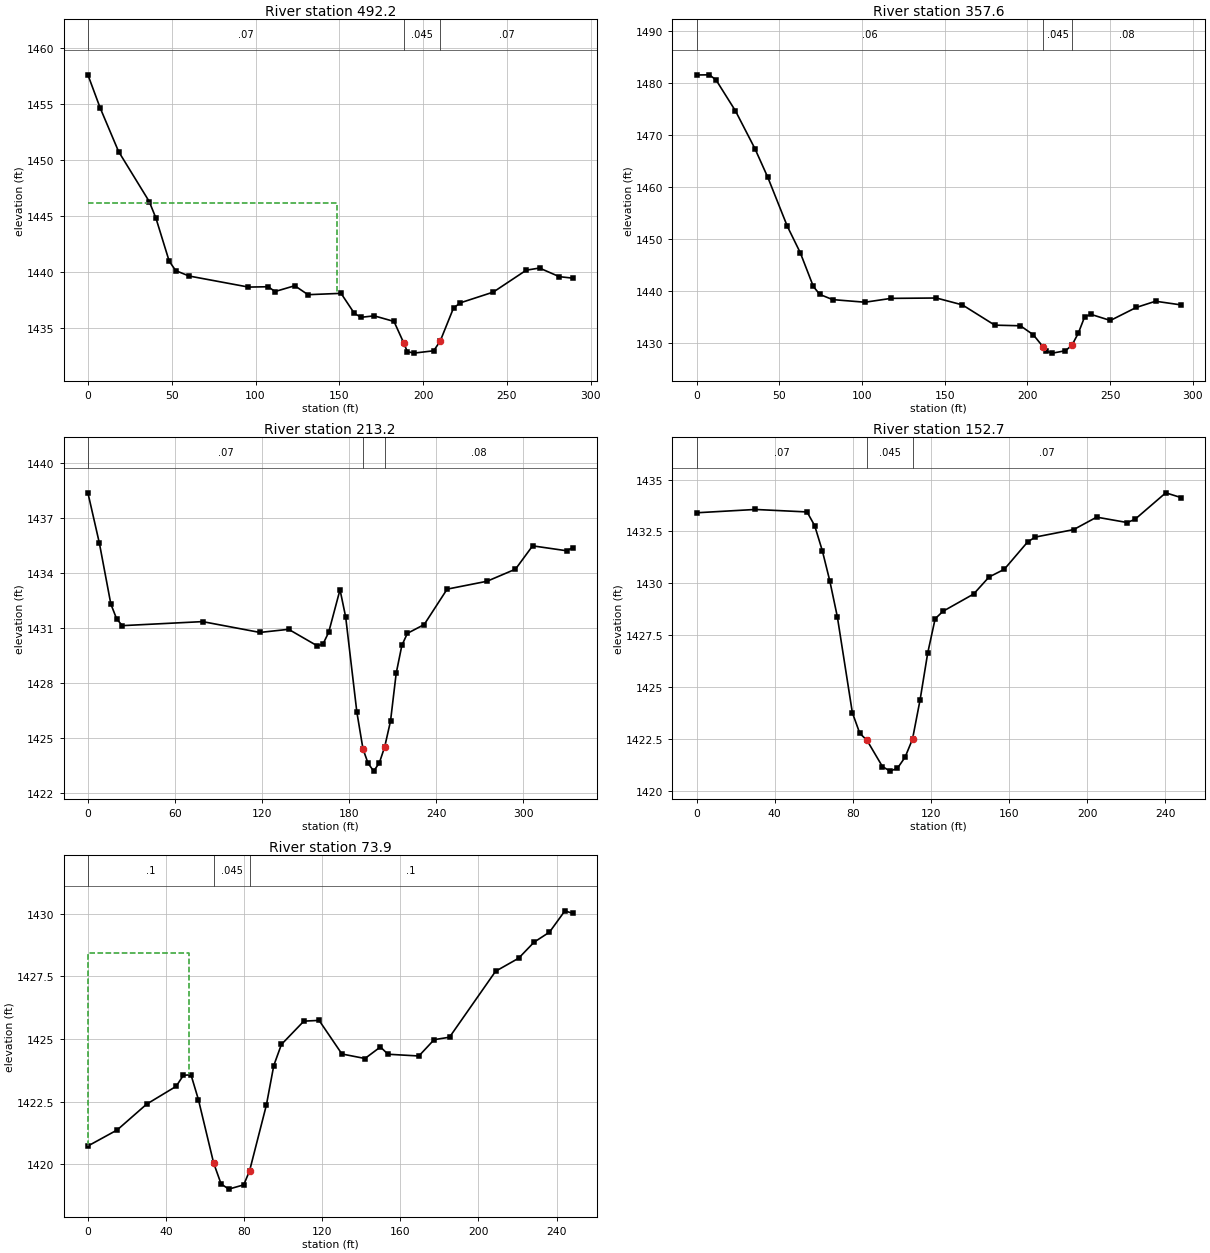
Type RM Length L Ch R = 1 ,492.2   ,134.7,134.5,133.8
XS GIS Cut Line= 3
     1797195.311      292145.056     1797224.824      292166.757
     1797410.588      292337.764
#Sta/Elev= 30
       0 1457.59     7.3 1454.64    18.3 1450.74    36.6 1446.27    40.6 1444.78
    48.5 1440.94    52.4  1440.1    60.3 1439.62    95.8 1438.63   107.6 1438.66
   111.6 1438.23   123.4 1438.75   131.3 1437.95     151 1438.07   158.9 1436.29
   162.9 1435.93   170.8 1436.06   182.6 1435.56   188.5 1433.61   190.5 1432.87
   194.4 1432.73   206.3 1432.94   210.2 1433.82   218.1 1436.76   222.1 1437.22
   241.8 1438.18   261.5 1440.14   269.4 1440.33   281.2 1439.56   289.1 1439.43
#Mann= 3 , 0 , 0
       0     .07       0   188.5    .045       0   210.2     .07       0
#XS Ineff= 2 , 0
          148.54 1446.11
Permanent Ineff=
       F       F
Bank Sta=188.5,210.2
XS Rating Curve= 0 ,0
Exp/Cntr=0.3,0.1

Type RM Length L Ch R = 1 ,357.6   ,148.4,144.5,140.1
XS GIS Cut Line= 3
     1797096.352      292223.181     1797218.748      292344.709
     1797309.026       292424.57
#Sta/Elev= 30
       0 1481.51     7.8 1481.54    11.8 1480.55    23.5 1474.62    35.3 1467.34
    43.1 1461.81    54.9  1452.4    62.7 1447.34    70.6 1440.85    74.5 1439.31
    82.3 1438.31   101.9 1437.81   117.6 1438.55     145 1438.62   160.7  1437.3
   180.3  1433.4   195.8 1433.28   203.6 1431.55   209.5 1429.23   211.4 1428.39
   215.2 1428.02     223 1428.48   226.9 1429.52   230.8 1431.85   234.7 1435.05
   238.6 1435.46   250.2  1434.3   265.8  1436.8   277.5    1438     293 1437.29
#Mann= 3 , 0 , 0
       0     .06       0   209.5    .045       0   226.9     .08       0
Bank Sta=209.5,226.9
XS Rating Curve= 0 ,0
Exp/Cntr=0.3,0.1

Type RM Length L Ch R = 1 ,213.2   ,81.1,60.4,39
XS GIS Cut Line= 4
     1797013.887      292369.882     1797142.359      292474.917
     1797198.783      292508.771     1797298.609       292487.07
#Sta/Elev= 30
       0 1438.38     7.9 1435.64    15.8 1432.32    19.8 1431.51    23.7 1431.14
      79 1431.36   118.5 1430.77   138.3 1430.94     158 1430.04     162 1430.14
   165.9 1430.78   173.7  1433.1   177.6 1431.61   185.3 1426.43   189.5 1424.43
     193 1423.64   196.9 1423.21   200.8 1423.66   204.5 1424.54   208.5 1425.94
   212.4 1428.54   216.3 1430.06   220.1 1430.72   231.7  1431.2   247.5 1433.13
     275 1433.56   294.6 1434.22   306.4 1435.49     330 1435.22   333.9 1435.39
#Mann= 3 , 0 , 0
       0     .07       0   189.5    .045       0   204.5     .08       0
Bank Sta=189.5,204.5
XS Rating Curve= 0 ,0
Exp/Cntr=0.3,0.1

Type RM Length L Ch R = 1 ,152.7   ,77.6,78.8,80
XS GIS Cut Line= 4
     1797060.762      292584.292     1797104.165      292561.723
     1797173.609      292538.285     1797296.873      292512.244
#Sta/Elev= 30
       0  1433.4    30.1 1433.56    56.6 1433.44    60.5 1432.78    64.4 1431.58
    68.2 1430.14    72.1  1428.4    79.8 1423.78    83.6 1422.79    87.3 1422.45
    95.2 1421.19    99.1 1420.97   102.9 1421.11   106.8 1421.64   110.6 1422.51
   114.5 1424.41   118.4 1426.66   122.2  1428.3   126.2 1428.66   141.9 1429.49
   149.8 1430.31   157.6 1430.68   169.5 1431.99   173.4 1432.23   193.1 1432.59
   204.9 1433.19   220.6 1432.93   224.6 1433.09   240.3 1434.36   248.2 1434.13
#Mann= 3 , 0 , 0
       0     .07       0    87.3    .045       0   110.6     .07       0
Bank Sta=87.3,110.6
XS Rating Curve= 0 ,0
Exp/Cntr=0.3,0.1

Type RM Length L Ch R = 1 ,73.9    ,67.9,73.9,80.5
XS GIS Cut Line= 4
      1797065.97      292655.473     1797109.373      292632.903
     1797178.817      292609.466     1797302.081      292583.424
#Sta/Elev= 30
       0 1420.73      15 1421.37    30.1  1422.4    45.2 1423.11    48.9 1423.55
    52.8 1423.57    56.6 1422.58    64.4 1420.05    68.2 1419.22    72.1 1419.01
    79.8 1419.18    82.8 1419.74    91.4 1422.36    95.2 1423.94    99.1 1424.78
   110.6 1425.71   118.4 1425.74   130.1  1424.4   141.9 1424.22   149.8 1424.68
   153.7 1424.39   169.5 1424.32   177.3 1424.97   185.2 1425.07   208.8  1427.7
   220.6 1428.22   228.5 1428.86   236.4 1429.26   244.3 1430.11   248.2 1430.01
#Mann= 3 , 0 , 0
       0      .1       0    64.4    .045       0    82.8      .1       0
#XS Ineff= 2 , 0
           51.59 1428.43
Permanent Ineff=
       F       F
Bank Sta=64.4,82.8
XS Rating Curve= 0 ,0
Exp/Cntr=0.3,0.1

Chan Stop Cuts=-1
Use User Specified Reach Order=0
Composite Channel Slope=5